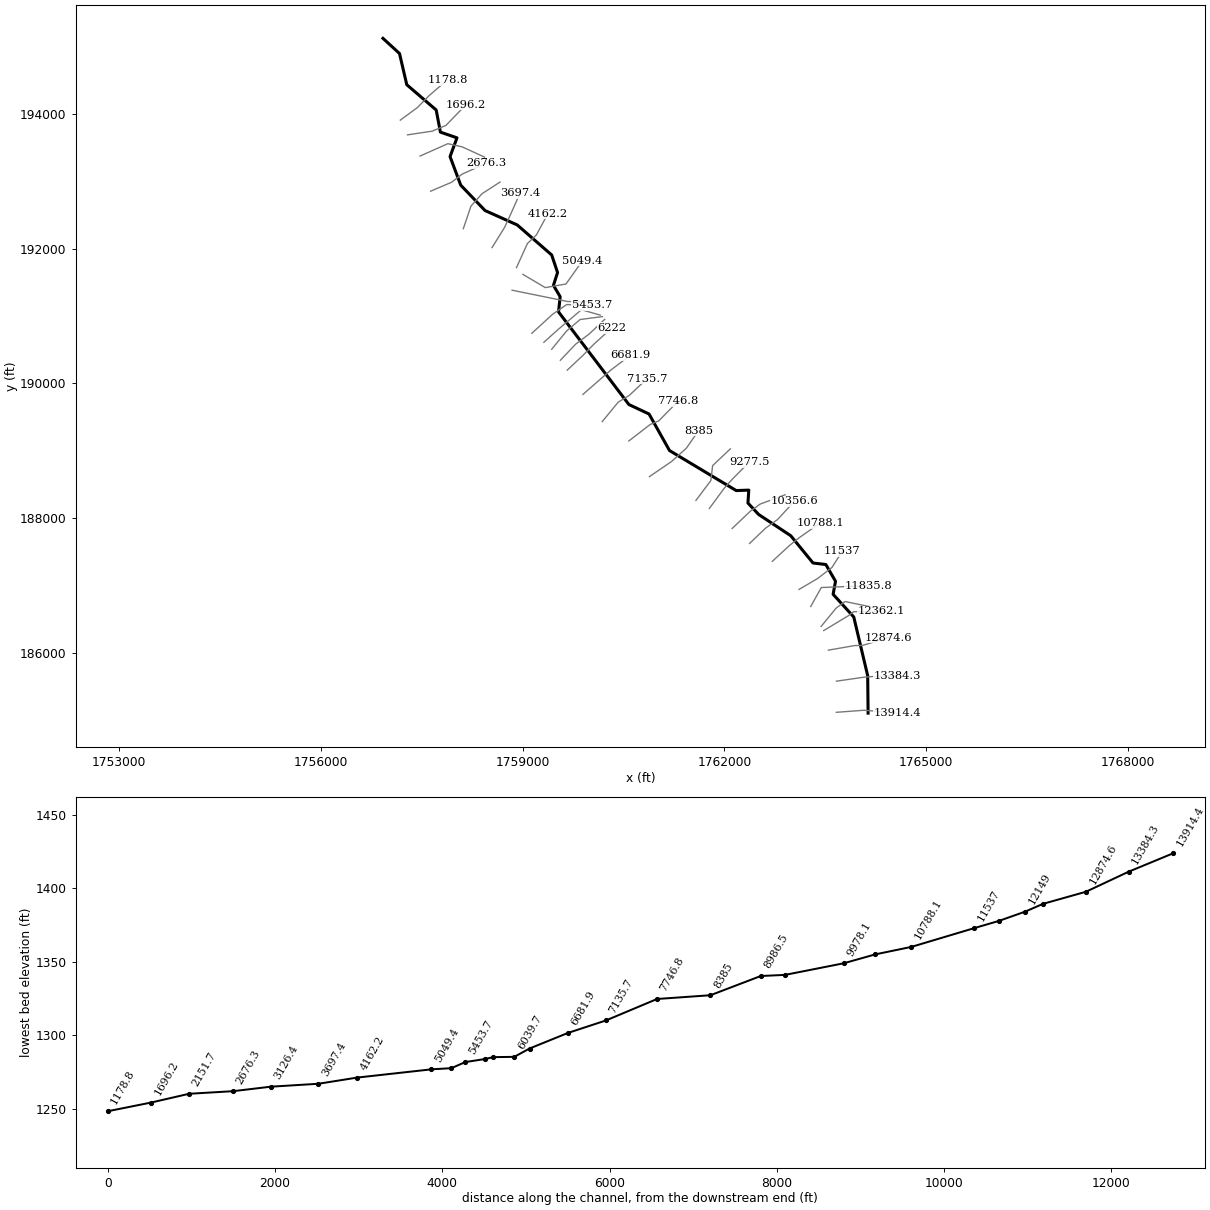
--- PadFk.prj (project) ---

Proj Title=PadFk
Current Plan=p01
Default Exp/Contr=0,0
English Units
Geom File=g01
Flow File=f01
Plan File=p01
BEGIN DESCRIPTION:
END DESCRIPTION:
DSS Export Rating Curves= 0
DSS Export Rating Curve Sorted= 0
DSS Export Volume Flow Curves= 0
DXF OffsetX= 0
DXF OffsetY= 0
DXF ScaleX= 0
DXF ScaleY= 0

--- PadFk.p01 (plan) ---

Plan Title=Floodplain
Program Version=4.00
Geom File=g01
Flow File=f01
K Sum by GR=0
Std Step Tol=0.01
Critical Tol=0.01
Num of Std Step Trials=20
Max Error Tol=0.3
Flow Tol Ratio=0.001
Split Flow NTrial=30
Split Flow Tol=0.02
Split Flow Ratio=0.02
Log Output Level=0
Friction Slope Method=1
Unsteady Friction Slope Method=2
Unsteady Bridges Friction Slope Method=1
Global Log Level=0
CheckData=False
Run HTab=0
Run UNet=0
Run PostProcess=0
UNET Theta=0
UNET Theta Warmup=0
UNET ZTol=0
UNET ZSATol=0
UNET MxIter=0
UNET MaxInSteps=0
UNET DtIC=0
UNET DtMin=0
UNET MaxCRTS=0
UNET WFStab=0
UNET SFStab=0
UNET WFX=0
UNET SFX=0
UNET DSS MLevel=0
UNET DZMax Abort=0
UNET Convert EG Bridges=0
UNET Use Existing IB Tables=0
UNET Froude Limit=0
UNET Froude Power=0
Write IC File=0
Echo Input=False
Echo Output=False
Write Detailed=0

--- PadFk.f01 (steady flow) ---

Flow Title=NFF Regression Equation
Program Version=4.00
Number of Profiles=1
Profile Names=P100yr
River Rch & RM=PadFk,Main      ,13914.4
542.0058
River Rch & RM=PadFk,Main      ,12149
582.0299
River Rch & RM=PadFk,Main      ,11537
720.2637
River Rch & RM=PadFk,Main      ,10788.1
767.3548
River Rch & RM=PadFk,Main      ,9978.1
838.9346
River Rch & RM=PadFk,Main      ,8986.5
916.0271
River Rch & RM=PadFk,Main      ,5453.7
1002.744
River Rch & RM=PadFk,Main      ,5287.3
1402.734
River Rch & RM=PadFk,Main      ,4162.2
1500.840
River Rch & RM=PadFk,Main      ,281.2
1640.237
Boundary for River Rch & Prof#=PadFk,Main      ,1
Up Type=0
Dn Type=3
Dn Slope=0.019066

--- PadFk.g01 (geometry) ---

Geom Title=USGS 10m DEM
Program Version=4.00

River Reach=PadFk           ,Main
Reach XY= 30
     1764136.026       185101.74     1764129.886      185658.483
     1763922.894      186530.304     1763616.127      186867.149
     1763651.946      187060.576     1763507.612      187309.784
     1763317.286      187331.784     1762986.102      187737.337
     1762509.804      188052.275     1762350.149      188222.164
     1762362.431      188414.568     1762176.228      188407.569
     1761184.332      189002.265     1760880.091      189545.273
     1760580.647      189685.662     1759534.792      191061.243
       1759558.8      191286.914     1759459.278      191456.714
     1759520.215      191647.055     1759432.979      191907.501
     1758920.198      192353.725     1758442.229       192567.61
     1758081.242      192943.875     1757922.292      193368.797
     1758025.154      193647.341     1757778.746      193732.197
      1757716.08      194060.805     1757279.078      194436.402
     1757171.017      194899.844     1756924.757      195125.333

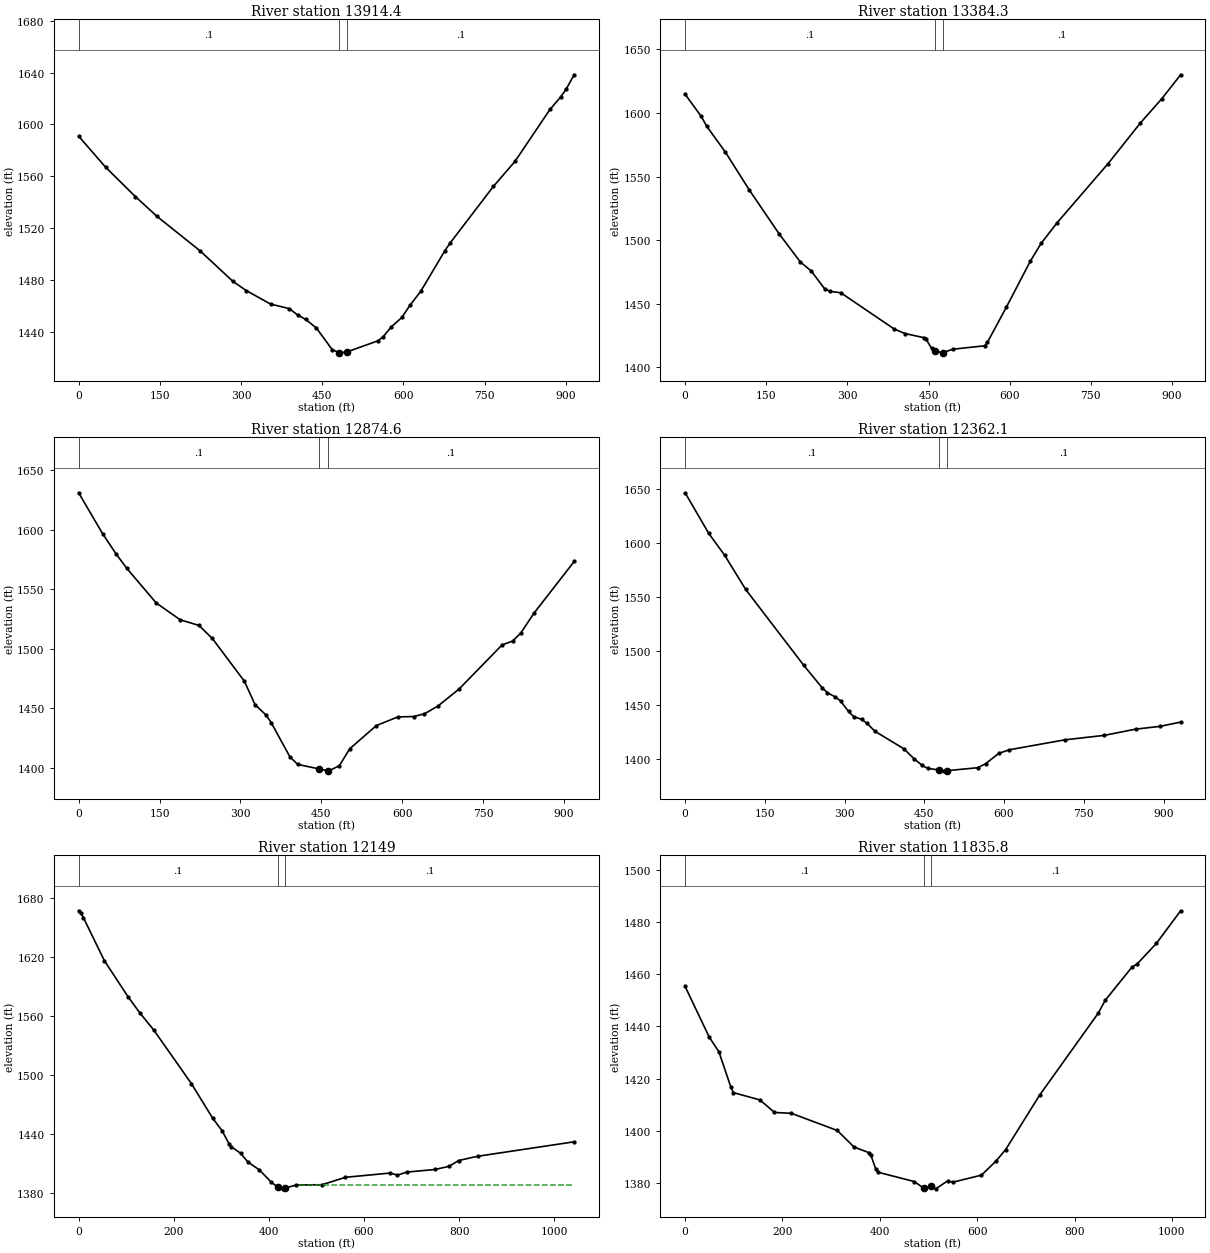
Type RM Length L Ch R = 1 ,13914.4 ,525.5,530.1,544.2
XS GIS Cut Line= 4
     1763663.638      185113.979     1764076.947      185144.859
      1764194.65      185135.367     1764575.766      185098.255
#Sta/Elev= 30
       0 1590.99    49.9    1567   104.9 1544.33   144.8 1529.06   224.7 1502.36
   284.6 1479.05   309.6 1471.82   354.5 1461.39   389.5 1457.82   404.5 1452.96
   419.4 1449.56   439.1 1442.96   468.6 1426.17   481.6 1423.85   483.3 1423.73
   496.6  1424.6   552.4 1432.92   562.4 1436.07   577.3 1443.61   597.2 1451.07
   612.1 1460.42     632 1471.21   676.8 1502.69   686.7  1508.7   766.3 1552.22
   806.1 1571.48   870.7 1611.57   890.6 1621.28   900.6 1627.22   915.5 1638.37
#Mann= 3 , 0 , 0
       0      .1       0   481.6    .045       0   496.6      .1       0
Bank Sta=481.6,496.6
XS Rating Curve= 0 ,0
Exp/Cntr=0.3,0.1

Type RM Length L Ch R = 1 ,13384.3 ,511.8,509.7,507.3
XS GIS Cut Line= 4
     1763664.976      185576.605     1764067.455      185634.657
     1764179.463       185644.15     1764575.952      185660.093
#Sta/Elev= 30
       0 1614.76    29.8 1597.35    39.7 1589.73    74.4 1569.26     119  1539.2
   173.6    1505   213.2 1482.64   233.1 1475.69   257.9 1461.66   267.8 1459.62
   287.6 1458.58   386.8 1429.91   406.6 1426.44   440.9 1423.24   445.7 1421.82
   455.5 1414.79   461.8 1412.73   475.1 1411.26   476.8 1411.45   494.6 1414.11
   553.8  1416.8   558.7 1419.48   593.5 1446.96   638.1 1483.38   657.9 1497.32
   687.7 1513.68   781.9 1560.23   841.5 1592.14   881.1 1611.25   915.9 1630.07
#Mann= 3 , 0 , 0
       0      .1       0   461.8    .045       0   476.8      .1       0
Bank Sta=461.8,476.8
XS Rating Curve= 0 ,0
Exp/Cntr=0.3,0.1

Type RM Length L Ch R = 1 ,12874.6 ,496.8,512.5,529.4
XS GIS Cut Line= 4
     1763545.684      186037.414     1763936.462      186105.471
     1764052.267       186107.37     1764441.513      186224.243
#Sta/Elev= 30
       0 1630.84    44.6 1596.44    69.4 1579.58    89.2 1567.54   143.8 1538.46
   188.4 1524.27   223.1 1519.61   247.9 1508.66   307.4 1472.76   327.2 1453.07
   347.1  1444.6     357 1438.16   391.7 1409.42   406.3 1403.02   446.6 1399.17
   461.6 1397.77   464.2 1397.63   483.5 1401.97   502.8 1416.18   552.1  1435.6
   591.8 1442.84   621.5 1443.18   641.3 1445.51   666.1 1451.89   705.8 1466.38
   785.1  1503.2   804.9 1506.52   819.8 1513.12   844.6 1530.01   918.9 1573.22
#Mann= 3 , 0 , 0
       0      .1       0   446.6    .045       0   461.6      .1       0
Bank Sta=446.6,461.6
XS Rating Curve= 0 ,0
Exp/Cntr=0.3,0.1

Type RM Length L Ch R = 1 ,12362.1 ,214.1,213.1,212
XS GIS Cut Line= 4
      1763476.73      186328.372     1763837.743       186545.91
     1763921.275      186608.558     1764327.541      186612.355
#Sta/Elev= 30
       0 1646.51    44.6 1608.89    74.4 1588.76     114 1557.11   223.1 1487.04
   257.8 1466.25   267.8 1461.58   282.6 1457.78   292.6 1453.93   307.4 1444.31
   317.4 1439.43   332.2 1437.03   342.2 1433.36     357 1426.06   411.6 1409.78
   431.4 1400.21   446.4 1394.38   456.3 1391.64   476.9 1390.31   486.1 1389.42
   491.9 1389.53   550.7 1392.32   565.5 1396.07   590.3 1405.65   610.1 1408.91
   714.2 1418.07   788.5 1422.22     848 1428.01   892.6 1430.48   932.2 1434.48
#Mann= 3 , 0 , 0
       0      .1       0   476.9    .045       0   491.9      .1       0
Bank Sta=476.9,491.9
XS Rating Curve= 0 ,0
Exp/Cntr=0.3,0.1

Type RM Length L Ch R = 1 ,12149   ,326.6,313.2,299.9
XS GIS Cut Line= 4
     1763437.849      186389.495     1763659.966      186660.972
     1763792.857      186759.691     1764307.335      186653.379
#Sta/Elev= 30
       0 1666.92     4.9 1664.53     9.9 1660.06    54.3    1616   103.8 1579.56
   128.4 1563.25   158.1 1545.56   237.1 1491.11   281.6 1456.11   301.4 1443.34
   316.2 1429.91   321.1    1427   340.9 1420.12   355.6 1411.52     380 1403.38
   404.3 1391.22   418.5 1385.84   428.7 1384.14   433.5 1384.84   457.9 1388.09
   511.4 1388.29   560.9 1395.87   655.1 1400.21     670 1398.04   689.8 1401.18
   749.2 1403.84     779 1407.07   798.8 1412.94   838.5 1417.24  1041.7 1431.98
#Mann= 3 , 0 , 0
       0      .1       0   418.5    .045       0   433.5      .1       0
#XS Ineff= 2 , 0
                          462.82         1388.15
Permanent Ineff=
       F       F
Bank Sta=418.5,433.5
XS Rating Curve= 0 ,0
Exp/Cntr=0.3,0.1

Type RM Length L Ch R = 1 ,11835.8 ,284.1,298.7,312.8
XS GIS Cut Line= 4
     1763283.398      186686.394     1763440.855      186967.797
     1763731.888      186979.023     1764135.799       186995.84
#Sta/Elev= 30
       0 1455.27    49.6 1435.88    69.4 1430.27    94.3 1416.61    99.2 1414.64
   153.8 1411.84   183.6 1407.06   218.3 1406.72   312.5 1400.17   347.1 1393.83
   376.8 1391.72   381.7 1390.69   391.6 1385.44   396.5 1384.18   470.6 1380.63
   490.5 1378.08   505.5 1378.76     515 1377.83   539.7 1380.92   549.5 1380.34
   608.8 1383.07   638.7 1388.44   658.6 1392.88   728.5 1413.73   848.3 1444.93
   863.2    1450   918.2 1462.71   928.1 1463.75   968.1 1471.72    1018 1484.22
#Mann= 3 , 0 , 0
       0      .1       0   490.5    .045       0   505.5      .1       0
Bank Sta=490.5,505.5
XS Rating Curve= 0 ,0
Exp/Cntr=0.3,0.1

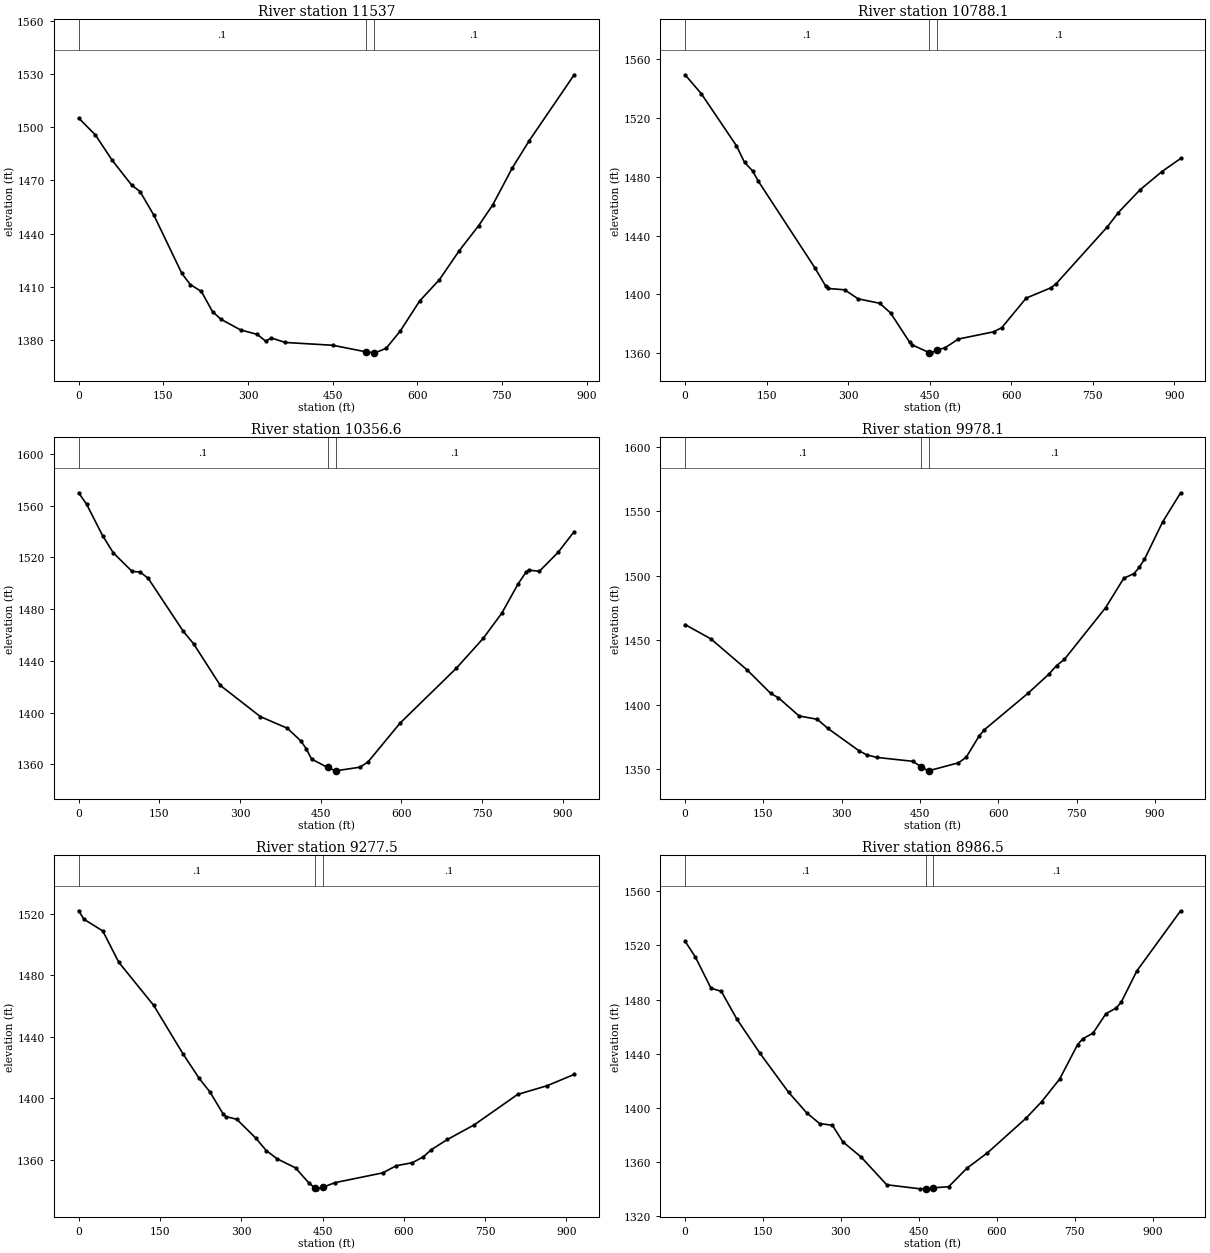
Type RM Length L Ch R = 1 ,11537   ,749.9,748.9,748.5
XS GIS Cut Line= 4
     1763109.222      186938.838     1763386.157      187101.896
      1763598.54      187265.419     1763754.212       187508.42
#Sta/Elev= 30
       0 1505.11    29.7 1495.57    59.3 1481.38    93.9 1467.35   108.8  1463.7
   133.5 1450.28   182.9 1417.57   197.8 1411.34   217.5 1407.41   237.3 1396.04
   252.2 1391.76   286.8 1385.78   316.4 1383.26   331.3 1379.47   341.2 1381.25
     366 1378.71   450.4 1377.12   509.1 1373.42   524.1  1372.9   524.9 1372.86
   544.7 1375.36   569.6 1385.03   604.3 1402.11   639.2 1414.04     674 1430.23
   708.8  1444.5   733.7 1456.18   768.5 1477.07   798.4 1492.36     878 1529.46
#Mann= 3 , 0 , 0
       0      .1       0   509.1    .045       0   524.1      .1       0
Bank Sta=509.1,524.1
XS Rating Curve= 0 ,0
Exp/Cntr=0.3,0.1

Type RM Length L Ch R = 1 ,10788.1 ,432.8,431.5,430.2
XS GIS Cut Line= 4
     1762712.276      187356.643     1762972.054      187595.748
     1763112.539      187707.756     1763422.274      187926.013
#Sta/Elev= 30
       0 1549.51    29.8 1536.64    94.5 1501.14   109.4 1489.78   124.3 1484.02
   134.3 1477.26   238.7 1418.06   258.6 1405.59   263.6 1403.96   293.4 1403.06
   318.3 1396.92   358.1 1393.88     378 1387.28     413 1367.38     418  1365.5
   448.9 1360.31   452.9 1360.13   463.9 1362.17   477.8  1363.5   502.8 1369.53
   567.6 1374.44   582.6  1377.3   627.5 1397.42   672.3 1404.32   682.3 1407.09
     777 1446.04     797  1455.7   836.9 1471.17   876.8 1483.48   911.6 1492.51
#Mann= 3 , 0 , 0
       0      .1       0   448.9    .045       0   463.9      .1       0
Bank Sta=448.9,463.9
XS Rating Curve= 0 ,0
Exp/Cntr=0.3,0.1

Type RM Length L Ch R = 1 ,10356.6 ,378.6,378.5,381.7
XS GIS Cut Line= 4
     1762374.081      187622.193     1762615.147      187852.038
     1762789.803      187977.335     1763043.245      188251.605
#Sta/Elev= 30
       0 1569.99    14.9 1561.07    44.7 1536.76    64.6  1523.5    99.4 1509.22
   114.3  1508.7   129.2 1503.96   193.9 1463.32   213.8 1453.23   263.5 1421.07
   338.1 1396.92   388.1 1387.98   413.1 1378.17   423.1 1372.24   433.1 1364.16
   462.8 1357.69   477.8 1355.05     478 1355.04     523 1357.85     538 1361.86
   597.8 1391.96   702.4 1434.38   752.2 1457.39     787 1476.97   816.9 1499.31
   831.8 1508.58   836.8 1510.21   856.7 1509.29   891.6 1523.95   921.5    1540
#Mann= 3 , 0 , 0
       0      .1       0   462.8    .045       0   477.8      .1       0
Bank Sta=462.8,477.8
XS Rating Curve= 0 ,0
Exp/Cntr=0.3,0.1

Type RM Length L Ch R = 1 ,9978.1  ,691.9,700.6,706.5
XS GIS Cut Line= 4
     1762115.399      187844.978     1762389.232       188104.53
     1762531.615      188207.046     1762902.833      188345.468
#Sta/Elev= 30
       0 1462.27    49.6 1451.11   119.2 1426.97   163.8 1408.98   178.7 1405.57
   218.4 1391.45   253.2 1388.89     273 1381.94   332.6 1364.62   347.5 1361.38
   367.4 1359.35   435.8 1356.35   451.7 1352.23     465 1348.96   466.7 1349.04
   523.5 1355.19   538.1 1359.39   562.6 1375.68   572.6 1380.62   656.7 1409.07
   696.4 1423.78   711.2 1430.46   726.1 1435.21   805.3 1475.38     840 1498.14
   859.8  1501.8   869.7 1506.71   879.6 1512.81   914.3 1541.66   948.9 1564.36
#Mann= 3 , 0 , 0
       0      .1       0   451.7    .045       0   466.7      .1       0
Bank Sta=451.7,466.7
XS Rating Curve= 0 ,0
Exp/Cntr=0.3,0.1

Type RM Length L Ch R = 1 ,9277.5  ,277.1,290.9,304.7
XS GIS Cut Line= 4
     1761776.441      188141.849     1761996.255      188440.555
     1762115.857      188575.344     1762371.863      188832.947
#Sta/Elev= 30
       0 1521.84     9.9 1516.32    44.5 1508.73    74.2 1488.31   138.5 1460.32
   192.8 1428.68   222.5 1412.86   242.3 1404.02     267 1389.52     272 1388.06
   291.8 1386.27   326.4 1374.22   346.1 1365.98   365.9 1360.67   400.1 1354.71
   424.4 1345.04   436.7 1341.37     439 1341.08   451.7 1342.26   473.1 1345.12
     561 1351.46   585.9 1356.09   615.8 1358.09   635.6 1361.81   650.6 1366.52
   680.4 1373.18   730.2 1382.76   809.8 1402.44   864.5 1408.14   914.2 1415.47
#Mann= 3 , 0 , 0
       0      .1       0   436.7    .045       0   451.7      .1       0
Bank Sta=436.7,451.7
XS Rating Curve= 0 ,0
Exp/Cntr=0.3,0.1

Type RM Length L Ch R = 1 ,8986.5  ,619.3,601.6,583.5
XS GIS Cut Line= 4
     1761577.319      188262.067     1761798.817      188556.359
     1761825.395      188778.477     1762088.405      189027.209
#Sta/Elev= 30
       0 1522.98    19.9 1511.26    49.8 1488.36    69.7 1486.04    99.6 1465.56
   144.4 1440.18   199.1 1411.61   233.9 1396.47   258.8 1388.51   283.7 1387.17
   303.6 1375.01   338.5 1363.92   388.2  1343.3   452.8 1340.31     463 1340.42
     478 1341.07   507.5 1341.88   542.3 1355.46   582.1 1366.88   656.5 1392.47
   686.2 1404.52     721 1421.25   755.7 1446.78   765.6 1451.01   785.4 1455.23
   810.2 1469.56   830.1 1473.74     840  1478.3   869.7 1501.09     954 1545.46
#Mann= 3 , 0 , 0
       0      .1       0     463    .045       0     478      .1       0
Bank Sta=463,478
XS Rating Curve= 0 ,0
Exp/Cntr=0.3,0.1

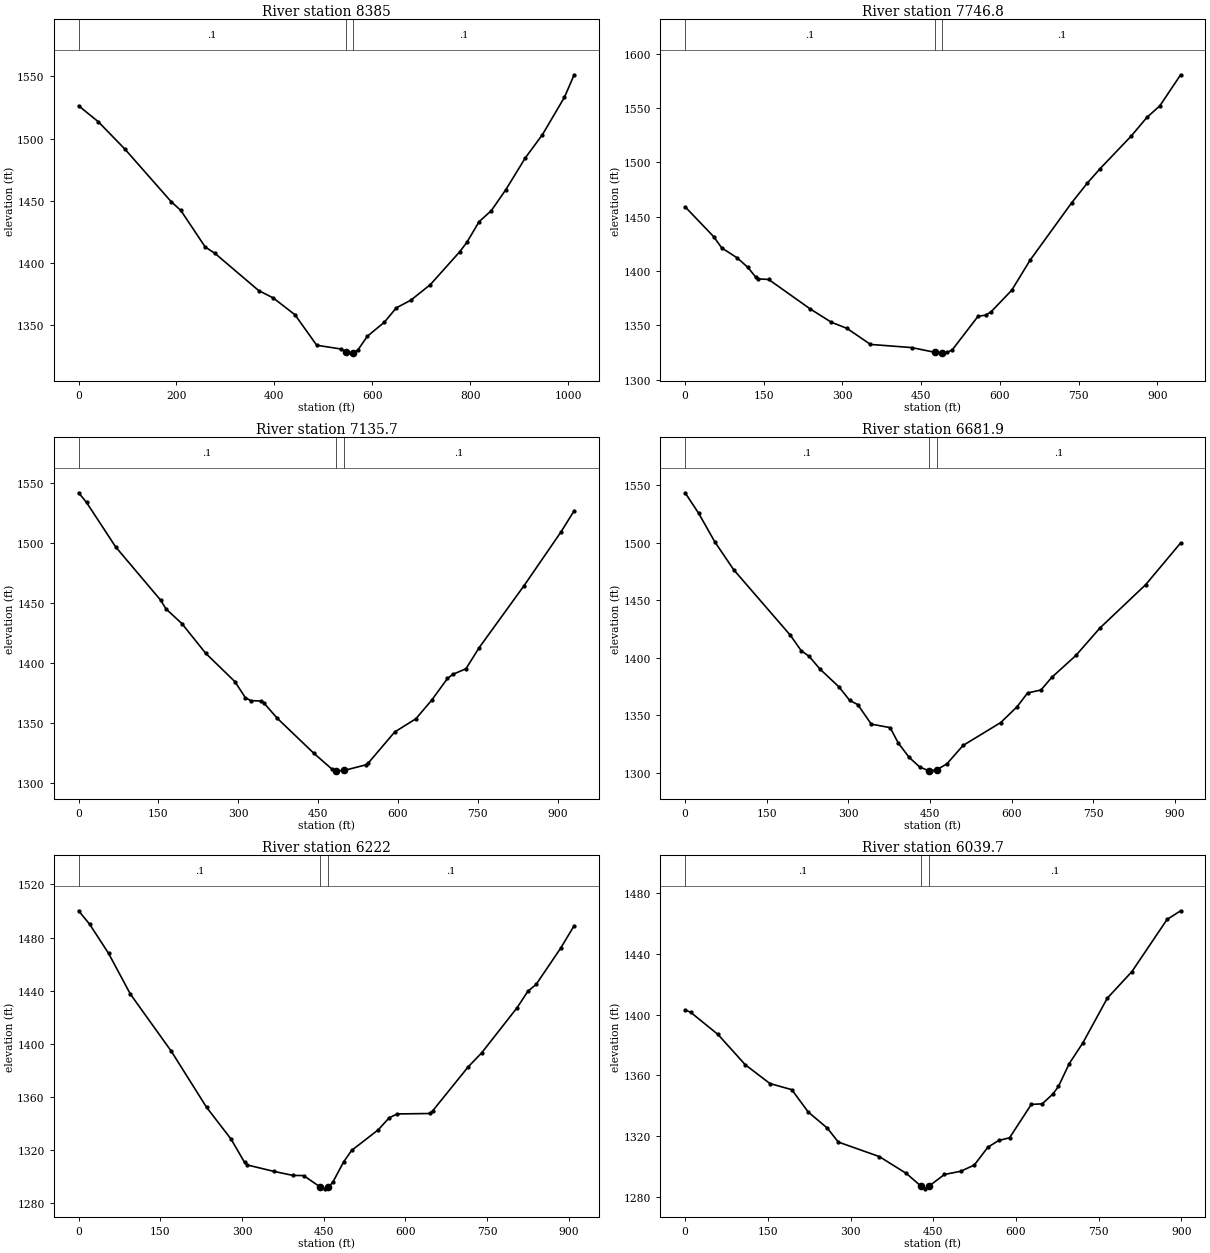
Type RM Length L Ch R = 1 ,8385    ,644.6,638.1,631.7
XS GIS Cut Line= 4
     1760885.548       188614.91     1761214.097      188839.227
     1761434.279      189036.756     1761616.566       189298.65
#Sta/Elev= 30
       0 1526.38    39.8 1513.66    94.5 1491.49     189 1449.13   208.9 1442.01
   258.6  1412.6   278.5 1407.44     368 1377.41   397.8 1371.47   442.2 1357.89
   486.6 1333.35   535.9 1330.34   545.5 1328.07   555.6 1327.23   560.5 1327.28
   570.4 1329.33   590.1 1340.65   624.6 1351.83   649.2 1363.49   678.8 1369.65
   718.6 1382.15   778.4 1408.53   793.3 1416.24   818.3 1432.93   843.2 1441.78
   873.1 1458.82     913 1484.48   947.9 1503.14   992.8 1533.26  1012.7 1551.38
#Mann= 3 , 0 , 0
       0      .1       0   545.5    .045       0   560.5      .1       0
Bank Sta=545.5,560.5
XS Rating Curve= 0 ,0
Exp/Cntr=0.3,0.1

Type RM Length L Ch R = 1 ,7746.8  ,608,611.1,614.2
XS GIS Cut Line= 4
     1760579.815      189144.723     1760895.158      189387.877
     1761024.253      189442.932     1761309.335      189732.059
#Sta/Elev= 30
       0 1459.07    54.8  1431.4    69.7 1421.26    99.6 1411.94   119.5 1403.38
   134.4  1394.5   139.4 1392.73   159.3 1392.18   238.9 1364.95   278.7 1352.85
   308.6 1347.18   353.4 1332.42   432.1 1329.52   475.5 1325.21   490.2 1324.68
   490.5 1324.68   499.8 1325.12   509.5 1327.57   558.4 1358.29   573.2 1359.42
   583.1 1362.35   622.7 1382.32   657.4 1409.76   736.6 1462.54   766.3 1480.62
   791.1 1494.15   850.5 1524.18   880.2 1541.24     905 1551.98   944.6  1580.5
#Mann= 3 , 0 , 0
       0      .1       0   475.5    .045       0   490.5      .1       0
Bank Sta=475.5,490.5
XS Rating Curve= 0 ,0
Exp/Cntr=0.3,0.1

Type RM Length L Ch R = 1 ,7135.7  ,450,453.8,457.6
XS GIS Cut Line= 4
     1760184.052      189431.673     1760420.548      189720.104
     1760587.611       189822.62     1760851.191        190070.7
#Sta/Elev= 30
       0 1541.55    14.9 1533.48    69.6 1496.47   154.2 1452.08   164.1 1444.89
     194 1432.68   238.7 1407.95   293.4 1384.43   313.3 1370.95   323.3 1368.56
   343.2 1368.14   348.1 1366.53     373 1353.92   441.6 1324.82   475.9 1311.54
   483.5 1310.19   485.7 1310.08   498.5 1310.38   539.6 1315.06   544.5 1316.73
   593.8 1342.41   633.5 1353.38   663.2 1368.84     693    1387   702.9 1390.38
   727.7 1395.06   752.5 1412.61   836.8 1464.22   906.2 1508.95     931 1526.61
#Mann= 3 , 0 , 0
       0      .1       0   483.5    .045       0   498.5      .1       0
Bank Sta=483.5,498.5
XS Rating Curve= 0 ,0
Exp/Cntr=0.3,0.1

Type RM Length L Ch R = 1 ,6681.9  ,457.8,459.9,461.9
XS GIS Cut Line= 3
     1759897.775       189836.51     1760312.337      190198.512
     1760600.068      190415.202
#Sta/Elev= 30
       0 1543.42    24.8 1525.68    54.5 1500.82    89.2 1476.54   193.4 1419.52
   213.2 1406.21   228.1 1401.08   247.9 1390.07   282.6 1374.66   302.5 1362.84
   317.3  1359.2   342.1 1342.21   376.8 1339.18   391.7 1325.85   411.5 1313.42
   431.4  1304.8   447.7  1301.7   451.2 1301.59   462.7 1302.61     481 1307.62
   510.7 1323.63     580 1343.59   609.6 1357.11   629.3 1369.29     654 1371.92
   673.7 1382.83   718.1 1401.92   762.5  1425.9   846.4 1463.52   910.6 1499.81
#Mann= 3 , 0 , 0
       0      .1       0   447.7    .045       0   462.7      .1       0
Bank Sta=447.7,462.7
XS Rating Curve= 0 ,0
Exp/Cntr=0.3,0.1

Type RM Length L Ch R = 1 ,6222    ,190.3,182.3,177.5
XS GIS Cut Line= 4
     1759663.425      190196.148     1759900.264      190418.574
     1760057.834      190579.942     1760323.929      190822.115
#Sta/Elev= 30
       0 1500.13      20 1490.13      55 1468.09      95 1437.48     170  1394.6
   234.9 1352.35   279.9 1328.43   304.9  1310.8   309.9 1308.93   359.2 1304.05
   393.6 1301.09   413.2 1300.95   443.7 1292.36   452.4 1290.98   458.7 1292.12
   467.1 1296.14   486.7 1311.21   501.4 1319.86   550.4 1335.41   570.4 1344.45
   585.4 1347.31   645.4 1347.65   650.4  1349.7   715.4 1382.67   740.3 1393.26
   805.3 1427.18   825.3 1439.68   840.3 1444.73   885.3 1471.95   910.2 1488.94
#Mann= 3 , 0 , 0
       0      .1       0   443.7    .045       0   458.7      .1       0
Bank Sta=443.7,458.7
XS Rating Curve= 0 ,0
Exp/Cntr=0.3,0.1

Type RM Length L Ch R = 1 ,6039.7  ,250,250.9,251.9
XS GIS Cut Line= 4
     1759561.721      190343.224     1759790.894      190583.983
     1759991.742      190734.619     1760220.914      190950.917
#Sta/Elev= 30
       0 1403.15     9.9 1401.63    59.5 1387.03   109.1 1367.04   153.8 1354.67
   193.5 1350.61   223.2 1335.94     258 1325.27   277.8 1316.12   352.1 1306.57
   401.3 1295.44     427  1287.3   435.8 1285.31     442 1287.02   470.2 1294.76
   499.8 1296.88   524.4 1300.97     549 1312.71   568.7 1317.16   588.4 1318.94
   627.8 1340.92   647.5 1341.28   667.2 1347.85     677 1352.76   696.7 1367.84
   721.3 1381.44   765.6 1410.87     810 1428.27     874 1462.74   898.6 1468.44
#Mann= 3 , 0 , 0
       0      .1       0     427    .045       0     442      .1       0
Bank Sta=427,442
XS Rating Curve= 0 ,0
Exp/Cntr=0.3,0.1

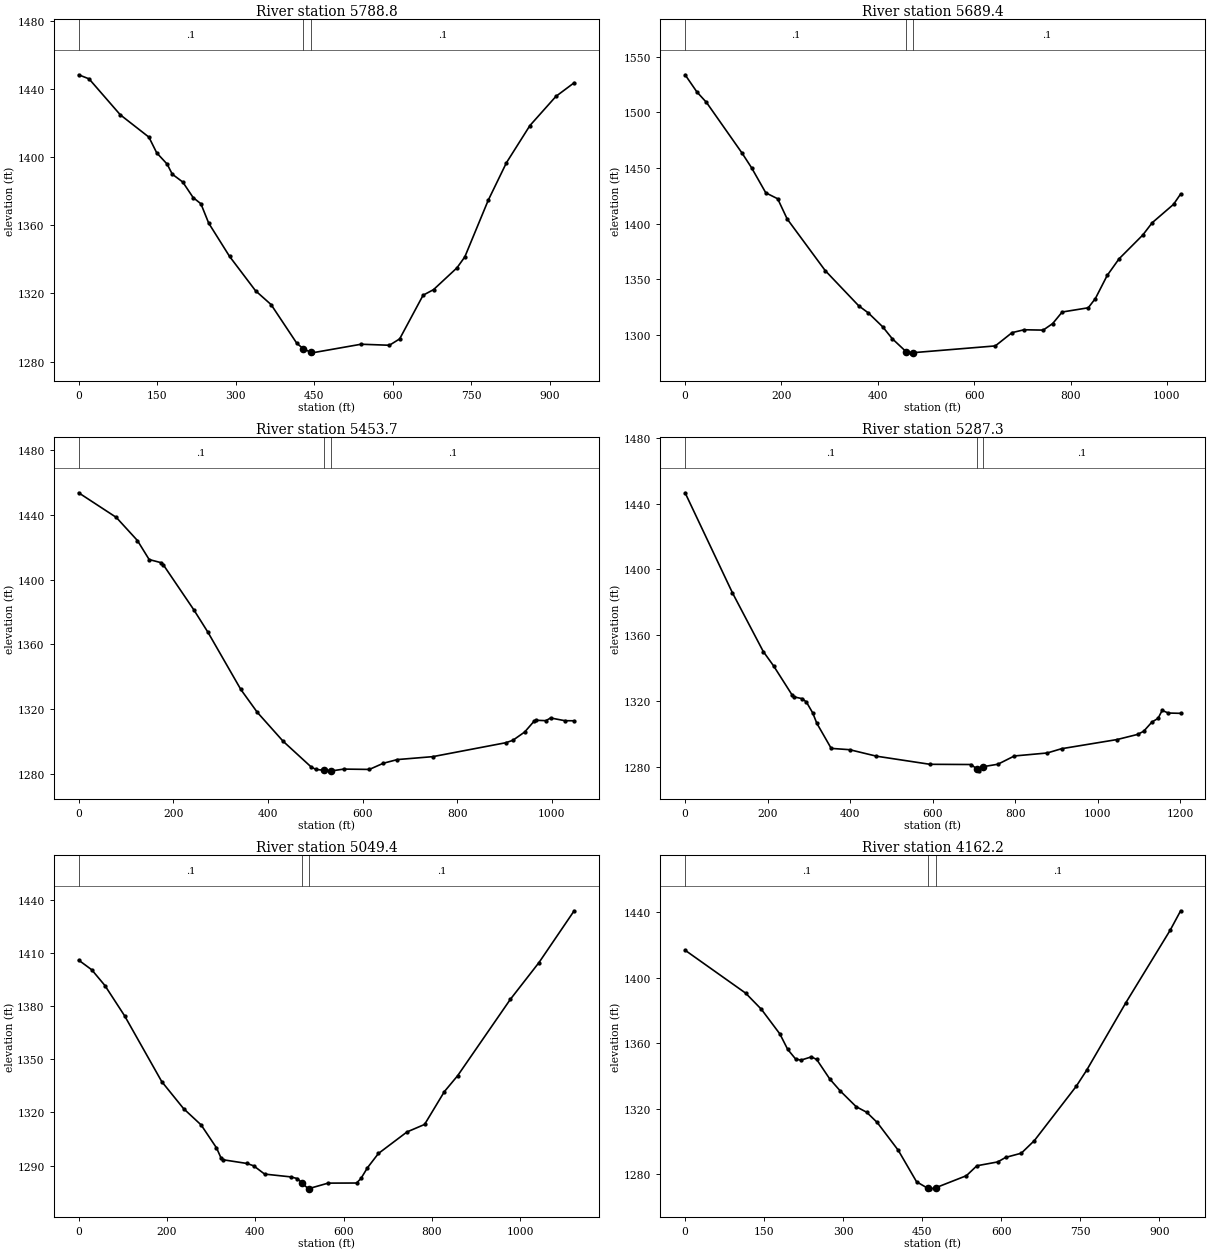
Type RM Length L Ch R = 1 ,5788.8  ,99.2,99.4,99.5
XS GIS Cut Line= 4
      1759433.08      190506.974     1759656.407      190780.406
     1759855.468      190948.423     1760186.092       190992.28
#Sta/Elev= 30
       0 1448.62    19.9 1446.22    79.6 1425.08   134.3 1411.95   149.2 1402.72
   169.1  1396.1     179 1390.15   198.9 1385.58   218.8 1376.43   233.7 1372.74
   248.6 1361.35   288.4 1341.82   338.1  1321.6   367.8 1313.47   416.9 1290.74
     429 1287.59     444 1285.34   446.4  1285.1   539.8 1290.16   593.9 1289.56
   613.5  1293.3   658.3 1318.99   678.2 1322.26     723 1335.08     738 1341.52
   782.8 1374.86   817.6 1396.92   862.4 1418.75   912.2 1435.94     947 1443.93
#Mann= 3 , 0 , 0
       0      .1       0     429    .045       0     444      .1       0
Bank Sta=429,444
XS Rating Curve= 0 ,0
Exp/Cntr=0.3,0.1

Type RM Length L Ch R = 1 ,5689.4  ,235.8,235.7,235.6
XS GIS Cut Line= 4
     1759316.882      190610.688     1759529.643      190801.524
     1759875.159      191093.884      1760154.23      191014.149
#Sta/Elev= 30
       0 1533.75    24.6 1518.27    44.4 1508.91   118.3 1463.31     138 1450.15
   167.5 1427.64   192.2  1422.3   211.9 1404.13   290.8 1357.76   360.4 1326.09
   380.3 1319.71   410.2  1307.2     430 1296.53   458.4 1285.01   469.8 1283.82
   473.4 1283.97   643.9 1290.04   678.7 1301.99   703.6 1304.56   743.3 1304.25
     763 1310.14   782.7 1320.51   836.8 1324.31   851.6 1332.61   876.2 1353.43
   900.8 1368.34     950 1389.71   969.6 1400.77  1013.9  1417.3  1028.6  1426.6
#Mann= 3 , 0 , 0
       0      .1       0   458.4    .045       0   473.4      .1       0
Bank Sta=458.4,473.4
XS Rating Curve= 0 ,0
Exp/Cntr=0.3,0.1

Type RM Length L Ch R = 1 ,5453.7  ,185.9,166.4,146.4
XS GIS Cut Line= 4
     1759137.332      190743.745     1759448.925      191028.541
     1759656.084      191170.745     1760029.469      191157.225
#Sta/Elev= 30
       0  1453.7    79.5 1438.49   124.2 1424.18     149 1412.42   173.8  1410.5
   178.8 1409.22   243.4 1381.32   273.2 1367.46   342.7 1332.06   377.4 1317.97
     432 1300.06   491.1  1284.2     501 1282.64   518.2 1282.08   533.2 1281.82
   535.4 1281.75   560.1 1282.83   614.3 1282.63   643.8 1286.44   673.4 1288.72
   748.1 1290.52   902.6 1299.14   917.5 1300.64   942.4 1305.76   962.4 1312.47
   967.3 1313.01   987.3 1312.78   997.2 1314.45  1027.1 1312.77    1047  1312.7
#Mann= 3 , 0 , 0
       0      .1       0   518.2    .045       0   533.2      .1       0
Bank Sta=518.2,533.2
XS Rating Curve= 0 ,0
Exp/Cntr=0.3,0.1

Type RM Length L Ch R = 1 ,5287.3  ,234.2,237.9,246.2
XS GIS Cut Line= 3
     1758844.431      191384.245     1759670.255      191216.125
     1760028.385      191214.857
#Sta/Elev= 30
       0 1446.52   114.7 1385.76   189.5 1350.06   214.4 1341.39   259.3 1323.69
   264.3 1322.51   284.2 1321.42   294.2 1319.31   309.2 1312.82   319.2  1306.5
   354.1 1291.24   398.9 1290.44   463.8  1286.5   593.4 1281.57   693.2 1281.44
   707.8 1278.57   713.1  1277.6   722.8 1280.15     758 1281.61   797.9 1286.63
   877.6 1288.45   912.4 1291.05  1046.7  1296.6  1096.4 1299.71  1111.4 1301.66
  1131.3 1307.23  1146.2  1309.5  1156.1 1314.32    1171 1312.72  1200.9 1312.53
#Mann= 3 , 0 , 0
       0      .1       0   707.8    .045       0   722.8      .1       0
Bank Sta=707.8,722.8
XS Rating Curve= 0 ,0
Exp/Cntr=0.3,0.1

Type RM Length L Ch R = 1 ,5049.4  ,872.1,887.2,902.2
XS GIS Cut Line= 4
     1759005.038      191619.312     1759337.764      191422.567
     1759645.442      191476.163     1759890.342       191821.57
#Sta/Elev= 30
       0 1406.13    29.7 1400.66    59.5 1391.77   104.1 1374.64   188.3 1337.41
   237.9  1322.1   277.5 1312.92   312.2 1299.99   322.1  1294.5   327.1 1293.25
   381.6 1291.14   396.5 1289.81   421.2 1285.15   480.7 1283.56   495.6 1282.59
   506.1 1280.03   520.4 1276.81   521.1 1276.92     565 1280.04   629.4  1280.1
   639.4 1282.66   654.2 1288.76     679 1296.81   743.7 1308.98   783.5 1313.22
   828.4  1331.8   858.3 1340.75   977.8 1383.97  1042.6 1404.75  1122.3 1434.02
#Mann= 3 , 0 , 0
       0      .1       0   506.1    .045       0   521.1      .1       0
Bank Sta=506.1,521.1
XS Rating Curve= 0 ,0
Exp/Cntr=0.3,0.1

Type RM Length L Ch R = 1 ,4162.2  ,456.2,464.8,473.3
XS GIS Cut Line= 4
     1758909.148      191718.983     1759072.654      192077.969
     1759205.545      192205.165     1759377.922      192523.257
#Sta/Elev= 30
       0 1416.71   114.8 1390.56   144.8 1380.67   179.8 1365.67   194.7 1356.22
   209.7 1350.38   219.7 1349.68   239.7 1351.69   249.7 1350.08   274.6 1338.15
   294.6 1330.83   324.6  1321.3   344.5 1317.91   364.5 1311.68   404.4 1294.73
   439.2 1275.51   460.7  1271.5   464.1 1271.21   475.7  1271.9   533.7 1279.22
   553.6 1285.28   593.3 1287.63   608.2 1290.38   637.9 1292.94   662.7 1300.63
     742 1333.69   761.8 1343.49   836.1 1384.62   920.4 1428.94   940.2 1440.76
#Mann= 3 , 0 , 0
       0      .1       0   460.7    .045       0   475.7      .1       0
Bank Sta=460.7,475.7
XS Rating Curve= 0 ,0
Exp/Cntr=0.3,0.1

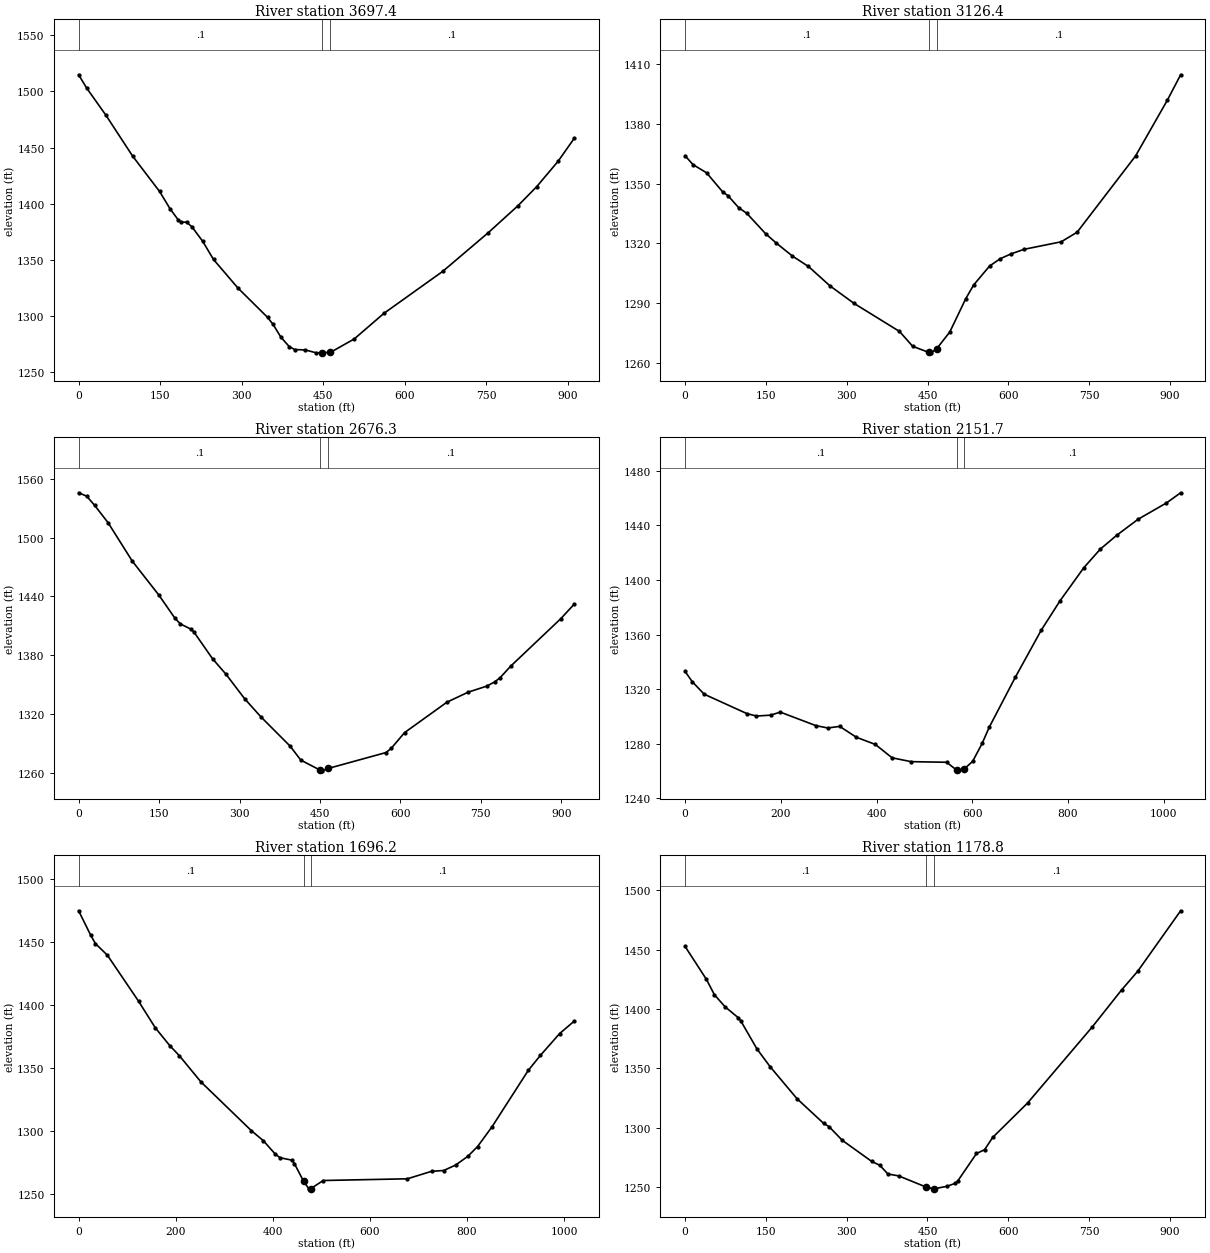
Type RM Length L Ch R = 1 ,3697.4  ,577.8,571,564.2
XS GIS Cut Line= 4
      1758546.94      192017.503     1758732.833      192317.173
     1758814.466      192493.728     1758963.545      192826.898
#Sta/Elev= 30
       0 1514.87    14.9 1502.93    49.7  1479.2    99.3 1442.44     149 1410.85
   168.9 1394.95   183.8 1385.25   188.7 1383.55   198.7 1383.43   208.6 1379.35
   228.5 1366.32   248.3 1350.21     293 1324.89   347.7 1298.66   357.6 1292.56
   372.6 1280.76   387.6 1272.62   397.5 1269.95   417.5 1269.54   437.4 1266.99
   448.3 1267.19   463.3 1267.35   507.3 1279.36     562  1302.2   670.5 1339.71
   754.3  1374.2   808.6 1398.07   843.1 1415.07   882.6 1437.77   912.2 1458.11
#Mann= 3 , 0 , 0
       0      .1       0   448.3    .045       0   463.3      .1       0
Bank Sta=448.3,463.3
XS Rating Curve= 0 ,0
Exp/Cntr=0.3,0.1

Type RM Length L Ch R = 1 ,3126.4  ,454.6,450.2,445.7
XS GIS Cut Line= 4
     1758119.637      192298.188     1758232.894      192633.096
     1758396.809      192816.463     1758665.229      192990.833
#Sta/Elev= 30
       0 1363.91    14.9 1359.44    39.8  1355.4    69.7 1345.81    79.7 1343.87
    99.6 1337.82   114.5 1335.04   149.4  1324.8   169.3 1320.08   199.2 1313.57
     229 1308.34   268.9  1298.6   313.7 1289.78   397.8 1275.75   422.4 1268.26
   452.1 1265.22   456.8 1264.99   467.1 1267.13   491.3  1275.5   520.8 1292.17
   535.5 1299.07   565.1 1308.59   584.7 1312.22   604.4 1314.62     629 1316.96
     698 1320.74   727.5 1325.55   835.9 1363.82     895 1391.86   919.6 1404.59
#Mann= 3 , 0 , 0
       0      .1       0   452.1    .045       0   467.1      .1       0
Bank Sta=452.1,467.1
XS Rating Curve= 0 ,0
Exp/Cntr=0.3,0.1

Type RM Length L Ch R = 1 ,2676.3  ,544.6,524.5,504.5
XS GIS Cut Line= 4
     1757632.394      192854.355      1757944.98      192987.323
     1758102.551      193108.823     1758454.245      193266.617
#Sta/Elev= 30
       0 1545.78      15 1542.33      30 1532.86      55 1515.17    99.9 1476.14
   149.9 1441.14   179.8 1417.57   189.8  1411.9   209.8 1406.47   214.8 1403.79
   249.8 1376.32   274.8 1360.54   309.7 1335.45   339.7 1317.16   394.4 1287.15
   414.3 1272.91   450.1 1262.71   454.1 1261.94   465.1 1264.34   573.3 1280.63
   583.1 1285.01   607.8 1300.95   686.9 1332.05   726.5 1342.26     761  1348.4
   775.9 1352.76   785.8 1356.91   805.5 1368.68   899.4  1417.4   924.1 1432.02
#Mann= 3 , 0 , 0
       0      .1       0   450.1    .045       0   465.1      .1       0
Bank Sta=450.1,465.1
XS Rating Curve= 0 ,0
Exp/Cntr=0.3,0.1

Type RM Length L Ch R = 1 ,2151.7  ,441.6,455.5,469.5
XS GIS Cut Line= 4
     1757476.695      193376.943     1757889.925      193560.652
     1758102.551      193513.191     1758434.778      193361.316
#Sta/Elev= 30
       0 1332.98    14.9  1325.5    39.8 1316.32   129.2 1302.09   149.1 1300.31
   178.9 1300.96   198.8 1303.19   273.3 1293.29   298.2 1291.57     323 1292.74
   357.8 1284.78   397.6  1279.5   432.4 1269.73     472 1266.91   546.3 1266.46
   568.6 1260.43   571.1 1260.18   583.6 1261.69   600.8 1267.11   620.6 1280.22
   635.4 1292.07   689.8 1328.61   744.1 1363.17   783.6  1384.8     833 1408.89
   867.5 1422.54   902.1 1432.77   946.5 1444.43  1005.8 1456.38  1035.4 1463.82
#Mann= 3 , 0 , 0
       0      .1       0   568.6    .045       0   583.6      .1       0
Bank Sta=568.6,583.6
XS Rating Curve= 0 ,0
Exp/Cntr=0.3,0.1

Type RM Length L Ch R = 1 ,1696.2  ,507.3,517.5,527.6
XS GIS Cut Line= 4
     1757290.017      193691.645     1757656.417        193746.7
     1757861.448      193832.129     1758158.872      194140.006
#Sta/Elev= 30
       0 1474.51    24.7 1455.28    34.6  1448.5    59.3 1439.28   123.5 1402.82
   158.1 1381.69   187.7  1367.7   207.5 1359.67     252  1338.9   355.7 1300.34
   380.4 1292.37   405.1 1281.71   414.9 1278.85   439.6  1276.9   444.6 1274.08
   463.2 1260.34   474.2  1254.2   478.2 1254.36   503.8  1260.8   677.2 1262.16
     727  1268.1   751.9 1268.72   776.8 1273.09   801.7 1279.99   821.6 1287.65
   851.5 1303.37   926.1 1348.03     951 1359.89   990.8 1377.24  1020.7 1387.04
#Mann= 3 , 0 , 0
       0      .1       0   463.2    .045       0   478.2      .1       0
Bank Sta=463.2,478.2
XS Rating Curve= 0 ,0
Exp/Cntr=0.3,0.1

Type RM Length L Ch R = 1 ,1178.8  ,549.8,536.7,523.6
XS GIS Cut Line= 4
     1757182.884       193910.44     1757438.096      194097.911
     1757608.956      194272.568     1757880.587      194507.282
#Sta/Elev= 30
       0 1452.69    39.6 1424.96    54.4 1411.98    74.2 1401.85      99 1392.49
   103.9 1389.54   133.6 1366.14   158.3 1351.06   207.8 1324.31   257.3 1303.46
   267.2 1300.79   291.9 1289.19   346.6 1271.38   361.6 1268.14   376.5  1260.8
   396.4 1259.24   446.9  1249.9   461.3  1248.3   461.9 1248.31   486.2 1250.43
   501.2 1252.88   506.2 1254.93     541 1278.11     556 1281.27     571 1291.63
   635.8 1320.67   755.4 1384.56   810.3 1415.98   840.2 1431.74     920  1482.8
#Mann= 3 , 0 , 0
       0      .1       0   446.9    .045       0   461.9      .1       0
Bank Sta=446.9,461.9
XS Rating Curve= 0 ,0
Exp/Cntr=0.3,0.1