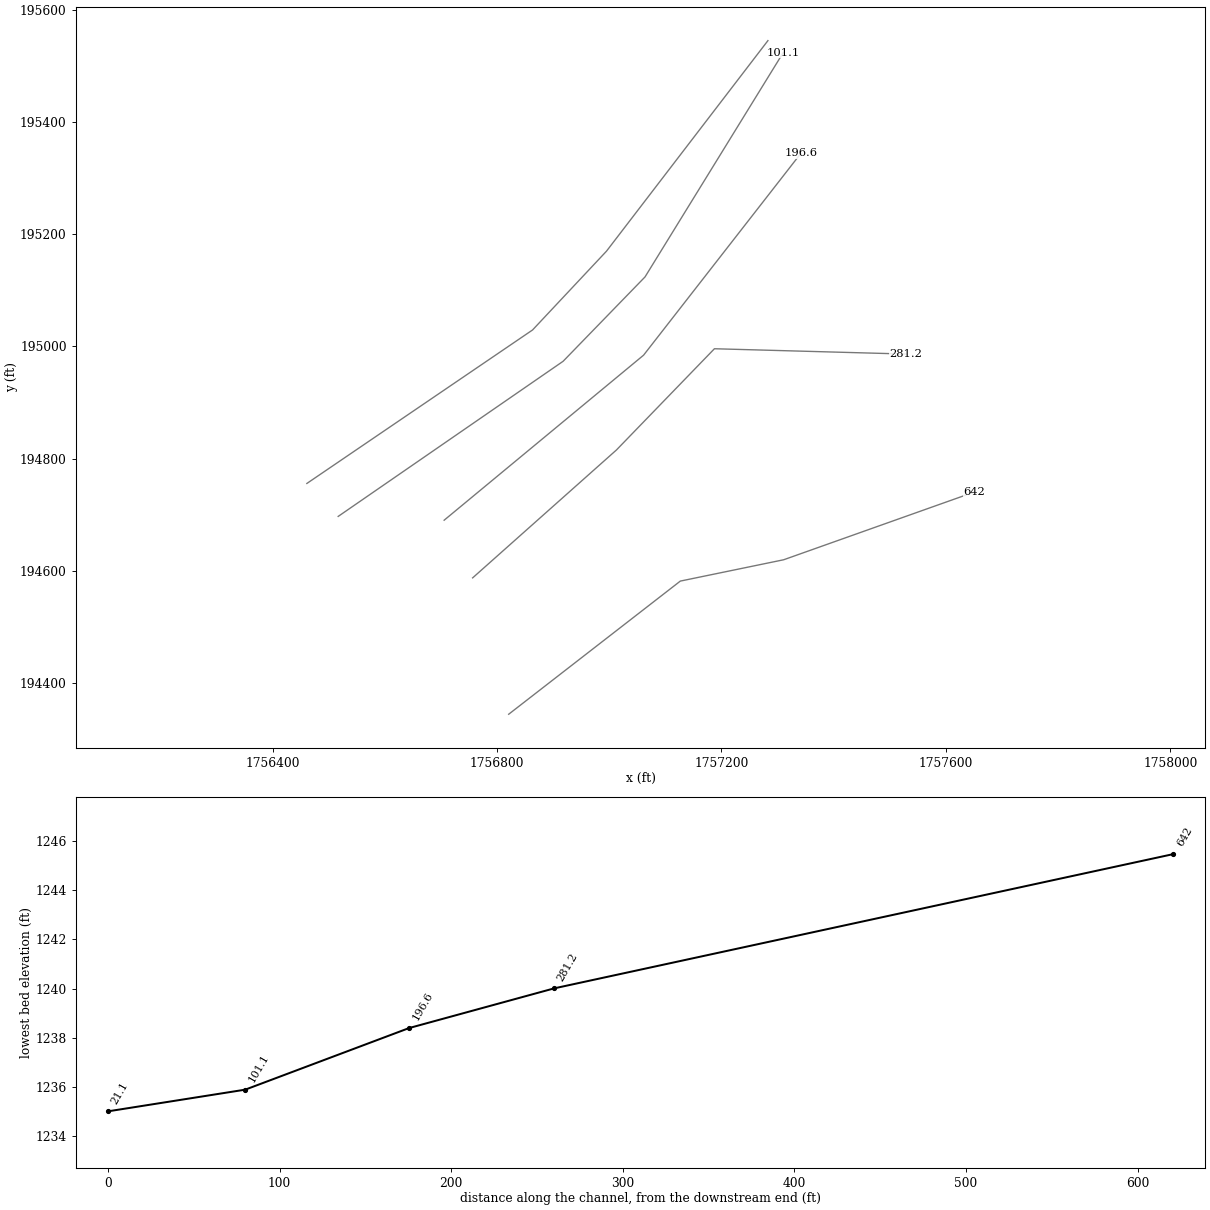
HEC-RAS study PadFk.prj: PadFk

--- PadFk.g01 (geometry) --- (continued)

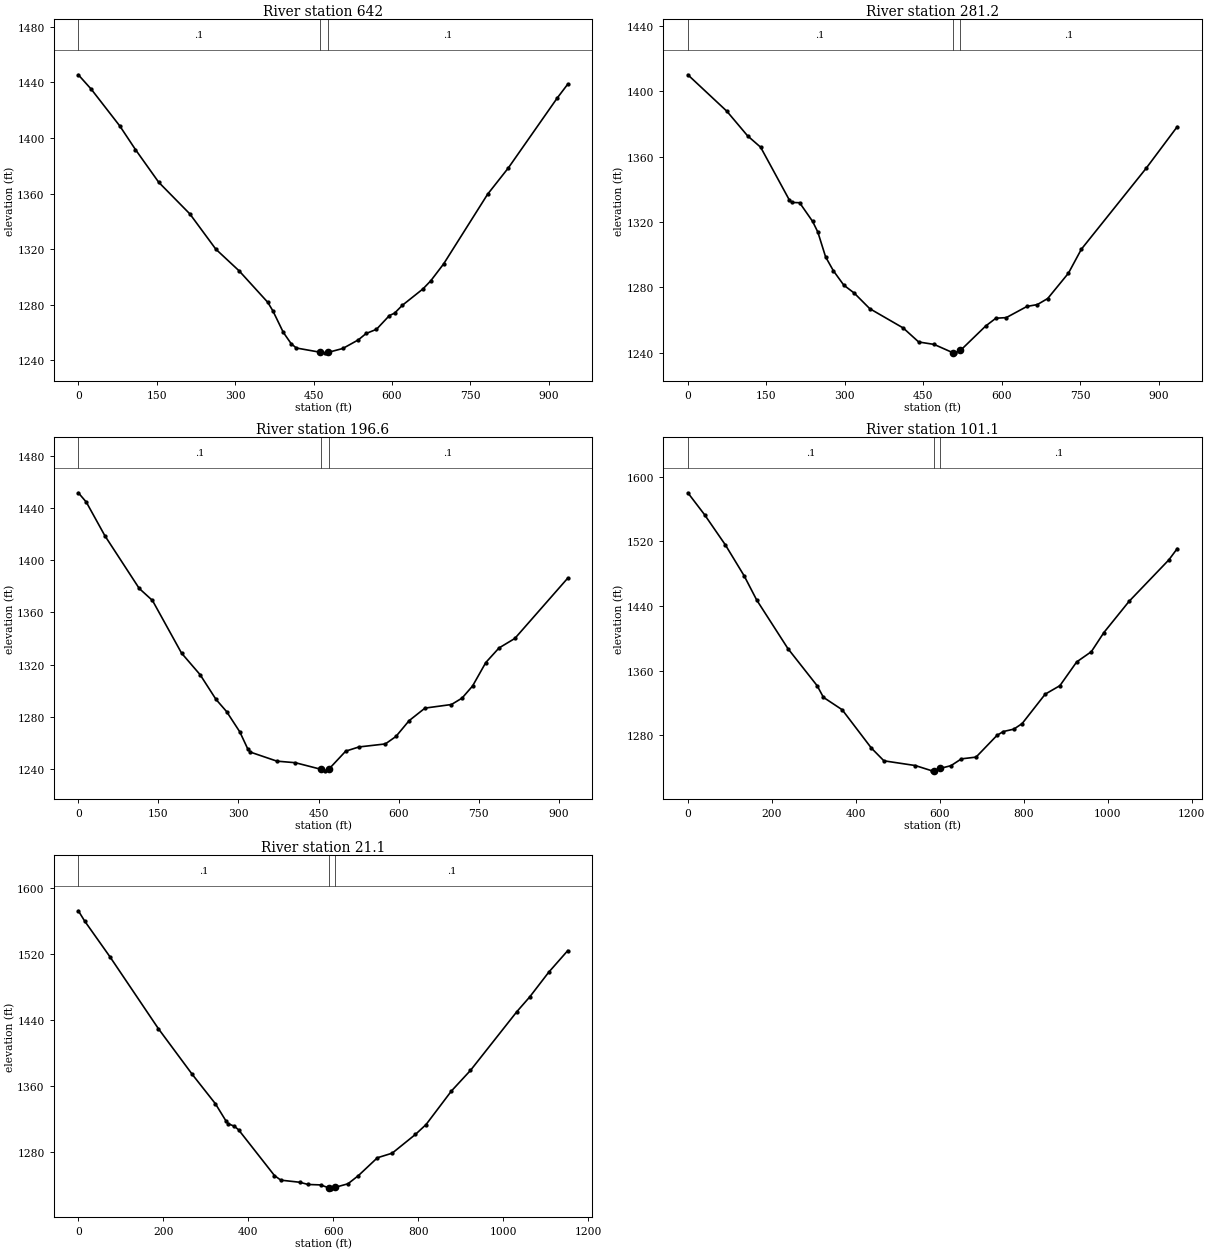
Type RM Length L Ch R = 1 ,642     ,347.2,360.9,374.5
XS GIS Cut Line= 4
     1756820.826      194344.829     1757126.752      194582.014
       1757310.9      194619.983     1757650.967      194740.715
#Sta/Elev= 30
       0  1445.5    24.8 1435.09    79.4 1408.63   109.2 1391.73   153.8 1368.15
   213.4 1345.36     263 1320.03   307.7 1304.38   362.3 1281.82   372.2 1275.58
     392 1260.21   406.9 1252.13   416.8 1248.95   462.1 1245.91   471.2 1245.46
   477.1 1245.72   505.8 1248.59   535.5 1254.79   550.4 1259.38   570.2 1262.38
   594.9 1272.28   604.8    1274   619.6 1279.64   659.2 1291.47     674 1297.27
   698.7 1309.47   782.7 1359.54   822.3 1378.44   916.2 1428.94     936 1438.73
#Mann= 3 , 0 , 0
       0      .1       0   462.1    .045       0   477.1      .1       0
Bank Sta=462.1,477.1
XS Rating Curve= 0 ,0
Exp/Cntr=0.3,0.1

Type RM Length L Ch R = 1 ,281.2   ,86.9,84.5,87.1
XS GIS Cut Line= 4
     1756756.555      194587.709     1757012.845      194815.522
     1757187.502      194995.874     1757529.221      194986.382
#Sta/Elev= 30
       0 1410.05    74.5 1387.79   114.3 1372.69   139.2 1365.75   193.8 1333.63
   198.8 1331.97   213.7 1331.81   238.5 1320.41   248.5 1313.91   263.4 1298.68
   278.3 1290.19   298.2 1281.41   318.1 1276.56   347.8 1267.03   411.8 1255.21
   441.4 1246.65   470.9 1245.16   506.2 1240.16   510.3 1240.01   521.2 1241.47
   569.4 1256.39     589 1261.19   608.8 1261.54   648.5  1268.4   668.3 1269.52
   688.1 1273.23   727.7 1288.72   752.5 1303.41   876.4 1352.91   935.8 1378.32
#Mann= 3 , 0 , 0
       0      .1       0   506.2    .045       0   521.2      .1       0
Bank Sta=506.2,521.2
XS Rating Curve= 0 ,0
Exp/Cntr=0.3,0.1

Type RM Length L Ch R = 1 ,196.6   ,93.1,95.5,93.1
XS GIS Cut Line= 3
     1756705.796      194690.449     1757061.247      194984.421
     1757341.412      195343.737
#Sta/Elev= 30
       0  1451.8    14.9 1444.67    49.6 1418.93   114.1 1378.37   138.9 1369.15
   193.4 1328.74   228.2 1312.17   257.9 1293.25   277.8 1283.87   302.6 1268.26
   317.4 1255.25   322.4 1252.76     372 1245.84   406.7 1244.63   453.8 1239.66
   461.3  1238.4   468.8 1239.46   500.9  1253.5   525.6 1256.72   575.2 1259.05
     595 1264.76   619.7  1276.9   649.5 1286.55     699  1289.3   718.8 1294.19
   738.6  1303.5   763.4 1321.53   788.1 1332.69   817.8    1340   916.9 1386.28
#Mann= 3 , 0 , 0
       0      .1       0   453.8    .045       0   468.8      .1       0
Bank Sta=453.8,468.8
XS Rating Curve= 0 ,0
Exp/Cntr=0.3,0.1

Type RM Length L Ch R = 1 ,101.1   ,79.6,80,80.4
XS GIS Cut Line= 4
     1756516.951       194697.21     1756917.794      194973.504
     1757063.815       195123.82     1757310.047      195523.231
#Sta/Elev= 30
       0 1580.26    39.7  1553.2    89.4 1515.69   134.1 1477.43   163.9 1447.53
   238.4 1387.25     308 1341.29   322.9 1326.92   367.6 1311.55   437.2 1264.03
     467 1248.31   541.7 1242.46   581.6  1235.9   585.5 1236.26   600.5 1238.88
   626.6 1242.28   651.5 1250.73   686.4  1252.9   736.3 1279.84   751.3 1284.58
   776.3 1287.53   796.2 1294.46   851.1 1330.87   886.1 1341.39     926 1370.76
     961 1383.48   990.9  1407.2  1050.8 1445.78  1145.6 1497.18  1165.6 1511.15
#Mann= 3 , 0 , 0
       0      .1       0   585.5    .045       0   600.5      .1       0
Bank Sta=585.5,600.5
XS Rating Curve= 0 ,0
Exp/Cntr=0.3,0.1

Type RM Length L Ch R = 1 ,21.1    ,23.5,21.1,18.6
XS GIS Cut Line= 4
     1756461.119      194755.904     1756863.393      195029.336
     1756995.099      195169.631     1757282.847      195544.705
#Sta/Elev= 30
       0 1571.98    14.9 1559.54    74.4 1516.24   188.6 1428.97     268 1373.77
   322.6 1338.11   347.4  1317.3   352.4 1314.02   367.3 1310.82   377.2  1306.5
   461.6 1251.08   476.5 1245.55   520.9    1243   540.7  1240.3   570.3 1239.78
   588.7 1236.29     595 1235.02   603.7 1236.78   634.4 1241.12   659.1 1251.08
   703.7 1272.68   738.6 1278.26   793.3    1301   818.2 1312.89   877.9 1353.58
   922.7 1378.52  1032.1 1449.88    1062  1467.5  1106.8 1497.49  1151.6 1523.69
#Mann= 3 , 0 , 0
       0      .1       0   588.7    .045       0   603.7      .1       0
Bank Sta=588.7,603.7
XS Rating Curve= 0 ,0
Exp/Cntr=0.3,0.1

Chan Stop Cuts=-1
Use User Specified Reach Order=0